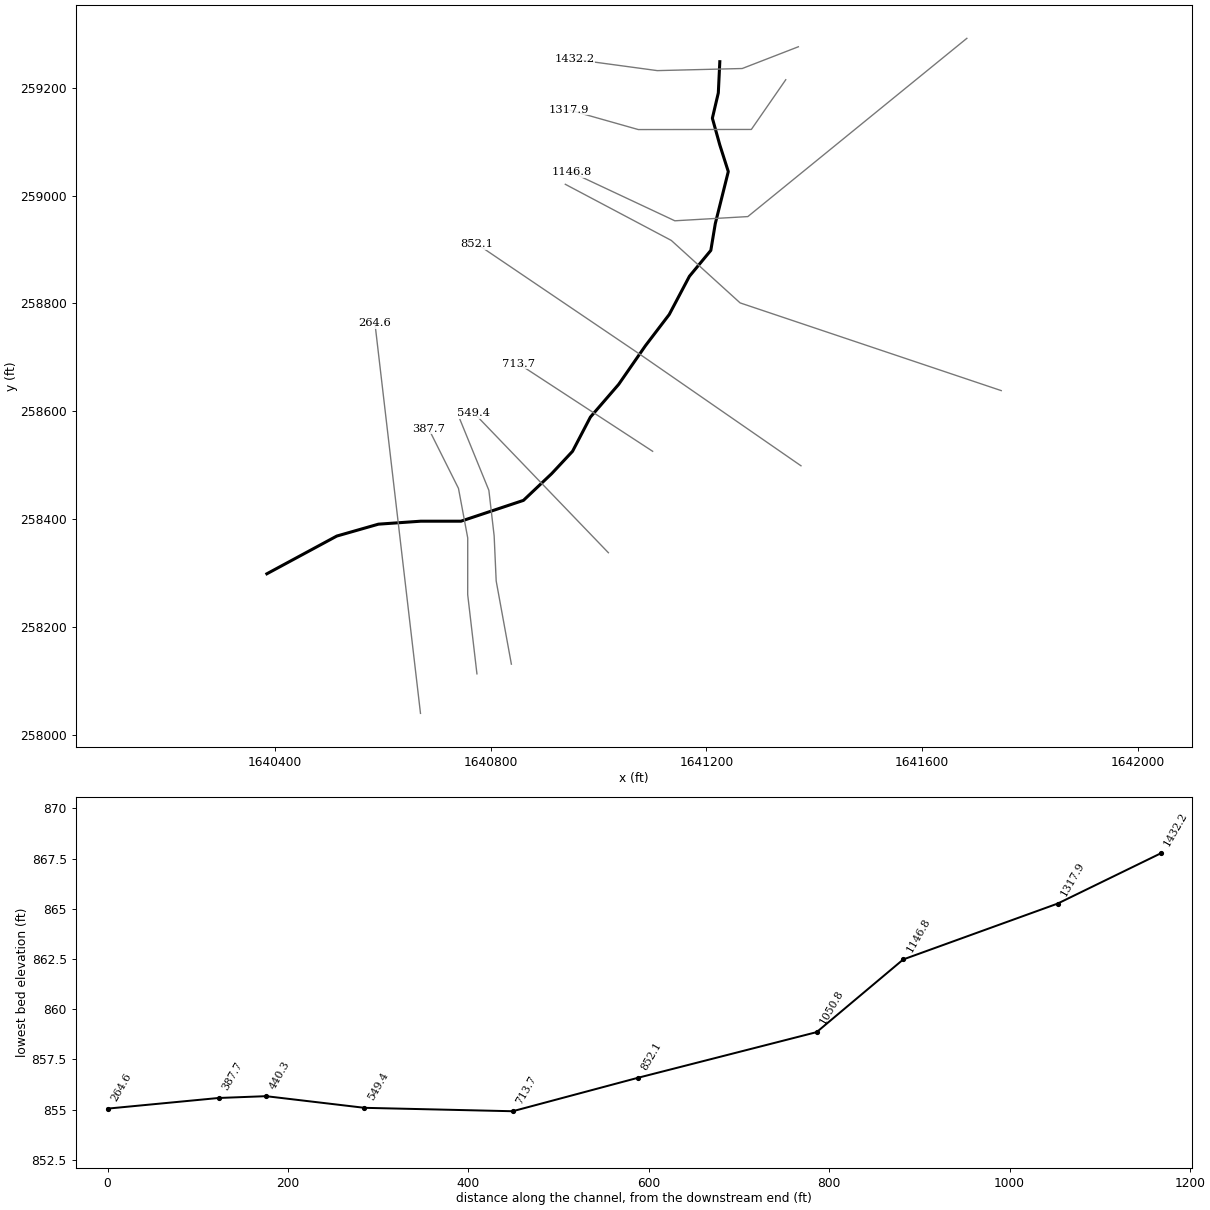
--- REDLICKRN.prj (project) ---

Proj Title=REDLICKRN
Current Plan=p01
Default Exp/Contr=0,0
English Units
Geom File=g01
Flow File=f01
Plan File=p01
BEGIN DESCRIPTION:
END DESCRIPTION:
DSS File=dss
DSS Export Rating Curves= 0
DSS Export Rating Curve Sorted= 0
DSS Export Volume Flow Curves= 0
DXF OffsetX= 0
DXF OffsetY= 0
DXF ScaleX= 0
DXF ScaleY= 0

--- REDLICKRN.p01 (plan) ---

Plan Title=Floodplain
Program Version=4.10
Short Identifier=Floodplain
Geom File=g01
Flow File=f01
Subcritical Flow
K Sum by GR= 0
Std Step Tol= 0.01
Critical Tol= 0.01
Num of Std Step Trials= 20
Max Error Tol= 0.3
Flow Tol Ratio= 0.001
Split Flow NTrial= 30
Split Flow Tol= 0.02
Split Flow Ratio= 0.02
Log Output Level= 0
Friction Slope Method= 1
Unsteady Friction Slope Method= 2
Unsteady Bridges Friction Slope Method= 1
Parabolic Critical Depth
Global Vel Dist= 0 , 0 , 0
Global Log Level= 0
CheckData=True
Encroach Param=-1 ,0,0, 0
Run HTab= 0
Run UNet= 0
Run PostProcess= 0
Run WQNet= 0
UNET Theta= 0
UNET Theta Warmup= 0
UNET ZTol= 0
UNET ZSATol= 0
UNET MxIter= 0
UNET MaxInSteps= 0
UNET DtIC= 0
UNET DtMin= 0
UNET MaxCRTS= 0
UNET WFStab= 0
UNET SFStab= 0
UNET WFX= 1
UNET SFX= 1
UNET DSS MLevel= 1
UNET DZMax Abort= 0
UNET Convert EG Bridges= 0
UNET Use Existing IB Tables= 0
UNET Froude Reduction=False
UNET Froude Limit= 0
UNET Froude Power= 0
UNET Time Slicing=0,0, 5
UNET Junction Losses=0
DSS File=dss
Write IC File= 0
Write IC File at Sim End=0
Echo Input=False
Echo Parameters=False
Echo Output=False
Write Detailed= 0
WQ AD Non Conservative
WQ ULTIMATE=-1
WQ Max Comp Step=1HOUR
WQ Output Interval=15MIN
WQ Output Selected Increments= 0
WQ Output face flow=0
WQ Output face velocity=0
WQ Output face area=0
WQ Output face dispersion=0
WQ Output cell volume=0
WQ Output cell surface area=0
WQ Output cell continuity=0
WQ Output cumulative cell continuity=0
WQ Output face conc=0
WQ Output face dconc_dx=0
WQ Output face courant=0
WQ Output face peclet=0
WQ Output face adv mass=0
WQ Output face disp mass=0
WQ Output cell mass=0
WQ Output cell source sink temp=0
WQ Output cell source sink nsm=0
WQ Output MaxMinRange=-1
WQ Daily Max Min Mean=-1
WQ Daily Range=0
WQ Daily Time=0
WQ Create Restart=0
WQ Fixed Restart=0
WQ System Summary=0
WQ Use Fixed Temperature=0
Sorting and Armoring Iterations= 10
XS Update Threshold= 0.02
Hydraulics Update Threshold= 0.02
Energy Slope Method= 1
Volume Change Method= 0
XS Weighting Method= 0
Number of US Weighted Cross Sections= 1
Number of DS Weighted Cross Sections= 1
Upstream XS Weight=0.25
Main XS Weight=0.5
Downstream XS Weight=0.25
Number of DS XS's Weighted with US Boundary= 1
Upstream Boundary Weight= 1
Weight of XSs Associated with US Boundary= 0
Number of US XS's Weighted with DS Boundary= 1
Downstream Boundary Weight= 0.5
Weight of XSs Associated with DS Boundary= 0.5
Sediment Output Level= 4
Mass or Volume Output= 0
Output Increment Type= 1
Profile and TS Output Increment= 10
XS Output Flag= 0
XS Output Increment= 10
Disregard all LS=0
Disregard all Conn=0
Disregard all Breaches=0
Disregard all Pumps=0

--- REDLICKRN.f01 (steady flow) ---

Flow Title=NFF Regression Equation
Program Version=4.10
Number of Profiles= 1
Profile Names=P100yr
River Rch & RM=REDLICKRN,Main            ,1432.2
408.8576
River Rch & RM=REDLICKRN,Main            ,1146.8
765.3195
River Rch & RM=REDLICKRN,Main            ,549.4
769.7879
River Rch & RM=REDLICKRN,Main            ,264.6
772.6857
Boundary for River Rch & Prof#=REDLICKRN,Main            , 1
Up Type= 0
Dn Type= 3
Dn Slope=0.00433
DSS Import GetInterval= 0
DSS Import GetPeak= 0
DSS Import FillOption= 0

--- REDLICKRN.g01 (geometry) ---

Geom Title=USGS 10m DEM
Program Version=4.10

River Reach=REDLICKRN       ,Main
Reach XY= 20
     1641224.955      259248.537     1641222.196      259190.593
     1641211.159      259143.686     1641224.955       259094.02
     1641240.696      259044.682     1641216.576      258948.086
     1641208.298       258898.42     1641168.566       258850.33
     1641131.141      258779.469     1641086.994      258721.526
     1641037.328      258649.785     1640984.903      258589.083
     1640951.792      258525.621     1640913.163      258484.232
     1640860.738      258434.566     1640744.851      258395.937
     1640670.352      258395.937     1640591.714      258390.419
     1640514.456      258368.345     1640384.791      258298.334

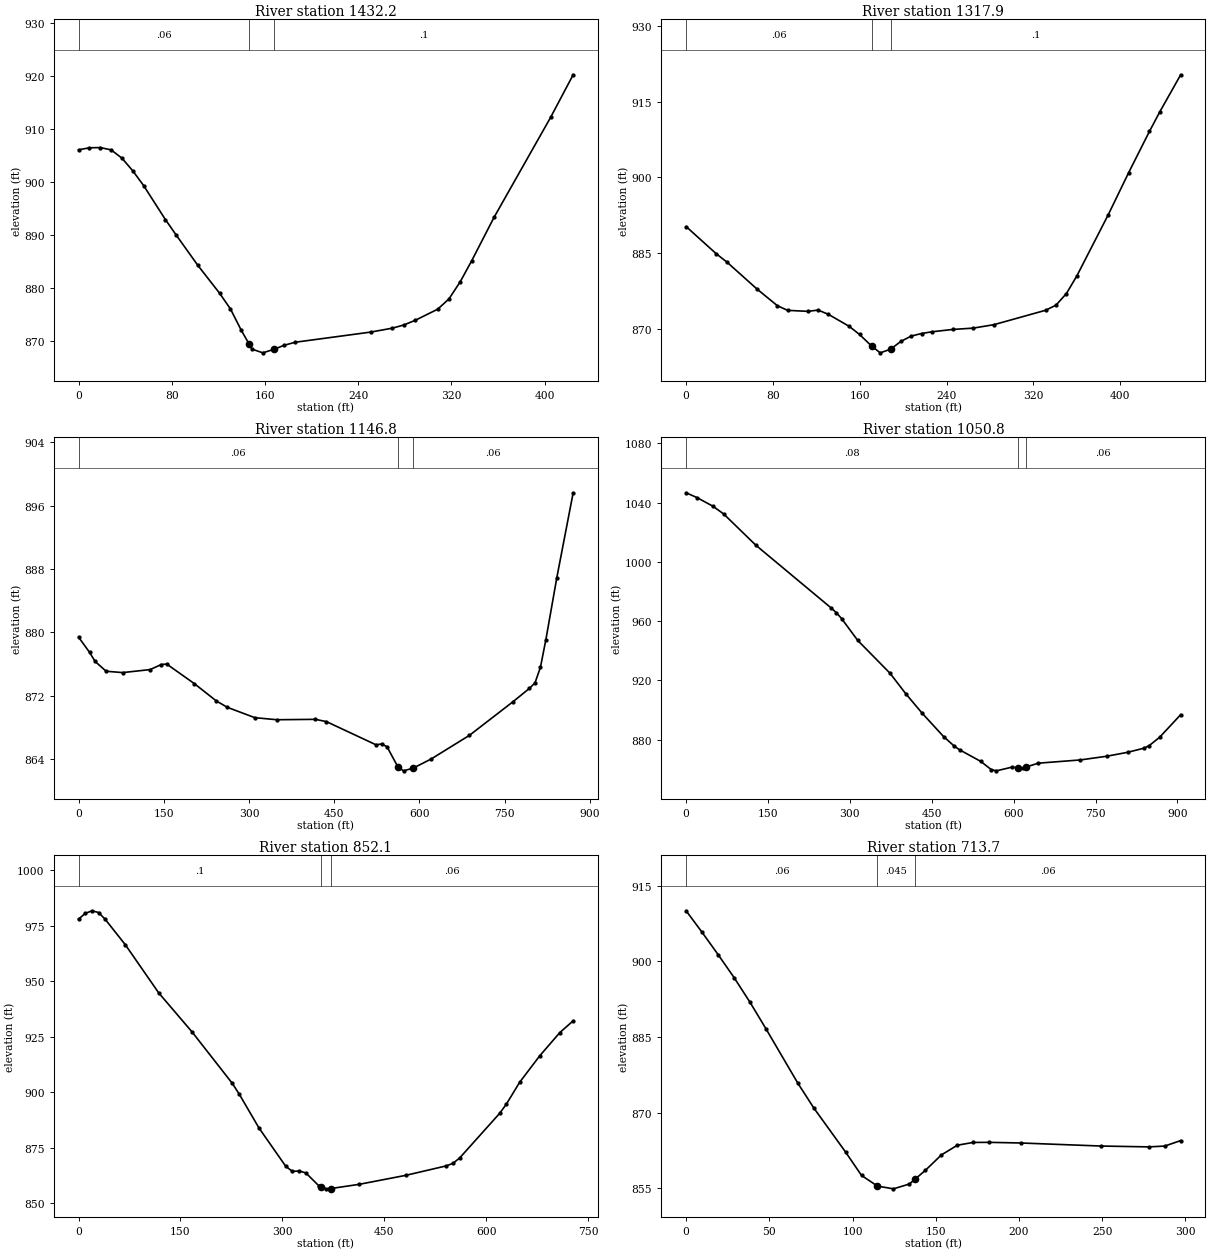
Type RM Length L Ch R = 1 ,1432.2  ,114.8,114.2,113.9
XS GIS Cut Line= 4
     1641370.693      259276.248     1641266.526      259235.884
     1641108.974      259231.977     1640955.328      259252.811
#Sta/Elev= 30
       0  906.08     9.3  906.46    18.6   906.5    27.9  906.07    37.2   904.5
    46.6  902.09    55.9   899.3    74.5  892.91    83.8  889.98   102.4  884.25
     121  879.01   130.3  876.05   139.5  872.06   146.4  869.39   148.8  868.46
   158.1  867.76   167.3   868.4   176.6   869.2   185.9  869.76   250.8  871.68
   269.3  872.42     279  873.01   288.7  873.88   308.1  875.99   317.8  877.93
   327.5  881.18   337.2  885.08   356.5  893.33     405  912.18   424.4  920.24
#Mann= 3 , 0 , 0
       0     .06       0   146.4    .045       0   167.3      .1       0
Bank Sta=146.4,167.3
XS Rating Curve= 0 ,0
Exp/Cntr=0.3,0.1

Type RM Length L Ch R = 1 ,1317.9  ,169.6,171.1,172.4
XS GIS Cut Line= 4
     1641347.255       259215.05     1641283.455      259122.812
     1641073.818      259122.602     1640944.911      259159.061
#Sta/Elev= 30
       0  890.28      28  884.85    37.4  883.28    65.4  877.89    84.1   874.6
    93.5  873.68   112.2  873.48   121.7  873.73   131.2  872.88   150.3  870.51
   159.8   868.9   171.1  866.58   178.9  865.26   188.4  865.98   197.9  867.52
   207.4  868.58     217  869.09   226.5  869.43   245.6  869.89   264.6  870.16
   283.7  870.84   331.4   873.7   340.9  874.71   350.5  877.01   360.1   880.5
   388.8  892.52   407.9  900.98     427  909.13   436.6  913.03   455.8  920.35
#Mann= 3 , 0 , 0
       0     .06       0   171.1    .045       0   188.4      .1       0
Bank Sta=171.1,188.4
XS Rating Curve= 0 ,0
Exp/Cntr=0.3,0.1

Type RM Length L Ch R = 1 ,1146.8  ,114.4,96,77.6
XS GIS Cut Line= 4
     1641683.193      259291.873     1641276.943      258961.144
     1641141.526      258953.331      1640950.12      259043.175
#Sta/Elev= 30
       0  879.38    19.4  877.45    29.1  876.31    48.5  875.07    77.6   874.9
   126.1  875.28   145.5  875.92   155.2  875.98   203.7  873.51   242.5  871.32
   261.9  870.51   310.4   869.2   349.2  868.94   417.1  868.99   436.5   868.7
   523.8  865.77   533.5  865.88   543.2  865.52   562.6  862.93   572.3  862.48
   589.4  862.83   620.7  863.97   688.3  866.97   765.2  871.23     794  872.91
   803.7   873.6   813.3  875.57   822.9  879.08   842.1  886.89   870.9  897.63
#Mann= 3 , 0 , 0
       0     .06       0   562.6    .045       0   589.4     .06       0
Bank Sta=562.6,589.4
XS Rating Curve= 0 ,0
Exp/Cntr=0.3,0.1

Type RM Length L Ch R = 1 ,1050.8  ,195.6,198.6,201.8
XS GIS Cut Line= 4
     1641746.995      258638.227      1641262.62      258800.988
     1641135.015      258916.873     1640938.401       259021.04
#Sta/Elev= 30
       0 1046.58    19.6 1043.39    49.1 1037.51    68.8 1032.28   127.8 1011.16
   265.3  968.93   275.2  965.64     285  961.55   314.4  946.89   373.4  924.78
   402.9  910.67   432.4  897.75   471.7  881.96   491.3  875.51   501.2  872.99
   539.7  865.24   558.9  859.69   568.4  858.86   597.2  861.38   607.5  860.94
   616.3  860.68   622.5  861.42   645.1  864.03   722.1  866.22   770.4  868.71
   809.1   871.4   838.2  874.12   847.8  875.78   867.2  881.48   905.9  896.78
#Mann= 3 , 0 , 0
       0     .08       0   607.5    .045       0   622.5     .06       0
Bank Sta=607.5,622.5
XS Rating Curve= 0 ,0
Exp/Cntr=0.3,0.1

Type RM Length L Ch R = 1 ,852.1   ,137.8,138.4,138.8
XS GIS Cut Line= 3
     1641375.492      258498.769     1641076.217      258705.958
     1640774.777      258910.035
#Sta/Elev= 30
       0  978.05     9.8   980.6    19.7  981.79    29.5     981    39.4  977.87
    68.9  966.46     118   944.8   167.2  927.17   226.3  904.06   236.1  899.41
   265.6  883.96     305  866.71   314.8  864.42   324.6  864.64   334.5  863.76
   354.2  857.78   356.5   857.5     364  856.58   371.5  856.72   413.2  858.62
   482.1  862.69   541.1  866.91   550.9  868.03   560.8  870.44   619.8  890.57
   629.6  894.69   649.3  904.59   678.8  916.48   708.3  926.92     728  932.24
#Mann= 3 , 0 , 0
       0      .1       0   356.5    .045       0   371.5     .06       0
Bank Sta=356.5,371.5
XS Rating Curve= 0 ,0
Exp/Cntr=0.3,0.1

Type RM Length L Ch R = 1 ,713.7   ,169.4,164.3,159.1
XS GIS Cut Line= 2
     1641100.372      258525.639     1640851.595       258688.14
#Sta/Elev= 24
       0     910     9.6  905.74    19.2  901.33    28.8  896.78    38.3  891.93
    47.9  886.67    67.1  875.87    76.7  870.95    95.8  862.22   105.4  857.58
     115  855.46   124.6  854.92   134.2  855.88   137.5  856.81   143.8  858.59
   153.4  861.64     163  863.56   172.5  864.11   182.1  864.13   201.3     864
   249.2   863.4     278  863.23   287.6  863.39   297.2  864.48
#Mann= 3 , 0 , 0
       0     .06       0     115    .045       0   137.5     .06       0
Bank Sta=115,137.5
XS Rating Curve= 0 ,0
Exp/Cntr=0.3,0.1

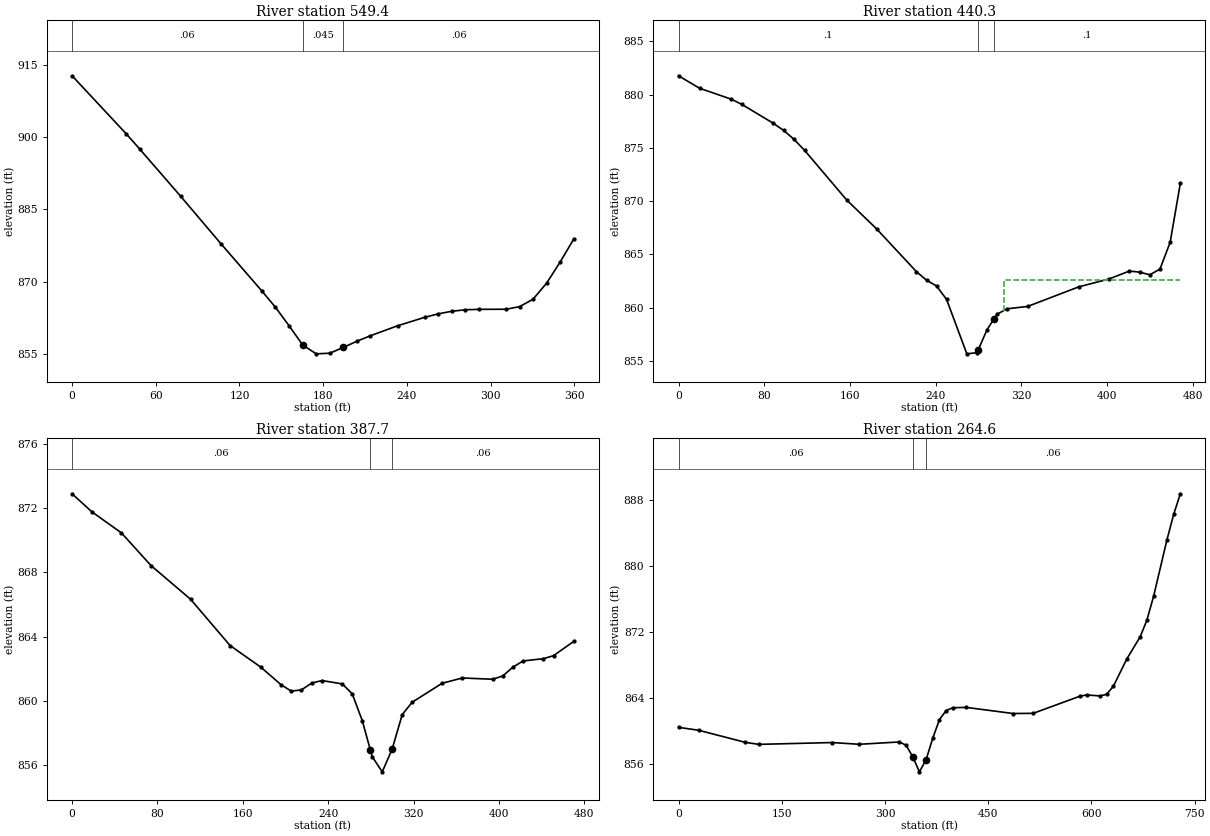
Type RM Length L Ch R = 1 ,549.4   ,124,109.1,94.2
XS GIS Cut Line= 2
     1641018.262      258337.446     1640768.938       258596.71
#Sta/Elev= 26
       0   912.7    38.9  900.65    48.6  897.48    77.8  887.75   106.9  877.84
   136.1   868.1   145.8  864.74   155.5  860.93   165.3  856.93     175  855.09
   184.7  855.22   194.4  856.41   204.2  857.71   213.9  858.84   233.3   860.9
   252.8  862.66   262.5  863.38   272.2  863.91   281.9  864.22   291.6  864.31
   311.1  864.33   320.8  864.87   330.5  866.42   340.2  869.75     350  874.17
   359.7  878.92
#Mann= 3 , 0 , 0
       0     .06       0   165.3    .045       0   194.4     .06       0
Bank Sta=165.3,194.4
XS Rating Curve= 0 ,0
Exp/Cntr=0.3,0.1

Type RM Length L Ch R = 1 ,440.3   ,51,52.6,54.2
XS GIS Cut Line= 5
     1640838.333      258130.693     1640810.157      258285.045
     1640806.386      258368.713     1640796.586      258453.239
     1640742.781      258585.174
#Sta/Elev= 30
       0  881.77    19.6   880.6      49  879.58    58.8   879.1    88.3  877.32
    98.1  876.64   107.9  875.79   117.7  874.76   156.9  870.11   184.8   867.4
     222  863.38   231.4  862.58   240.7  862.04   250.1  860.78     269  855.67
   278.5  855.78   279.4  855.99   287.9  857.95   294.4  858.95   297.4  859.41
   306.8   859.9   325.8  860.12   373.2  861.95   401.7   862.7   420.7  863.44
   430.2  863.34   439.7  863.09   449.2  863.62   458.7  866.14   468.2  871.67
#Mann= 3 , 0 , 0
       0      .1       0   279.4    .045       0   294.4      .1       0
#XS Ineff= 2 , 0
                          303.52          862.64
Permanent Ineff=
       F       F
Bank Sta=279.4,294.4
XS Rating Curve= 0 ,0
Exp/Cntr=0.3,0.1

Type RM Length L Ch R = 1 ,387.7   ,124.7,123.2,121.6
XS GIS Cut Line= 5
      1640774.46      258112.723     1640757.309      258259.725
     1640757.368      258364.923     1640740.218      258456.799
     1640685.033      258567.205
#Sta/Elev= 30
       0  872.88    18.5  871.76    46.2  870.45      74  868.41     111  866.32
     148  863.44   176.7   862.1   195.8     861   205.4   860.6   214.9  860.68
   224.5   861.1   234.1  861.26   253.2  861.05   262.5  860.43   271.9  858.76
   279.4  856.95   281.2  856.52   290.6  855.58   299.9     857   309.3  859.14
   318.6  859.91   346.7  861.09   365.6  861.42   394.1  861.34   403.6  861.55
   413.1   862.1   422.6  862.48   441.6  862.62   451.1  862.81   470.1   863.7
#Mann= 3 , 0 , 0
       0     .06       0   279.4    .045       0   299.9     .06       0
Bank Sta=279.4,299.9
XS Rating Curve= 0 ,0
Exp/Cntr=0.3,0.1

Type RM Length L Ch R = 1 ,264.6   ,256,264.6,273.1
XS GIS Cut Line= 2
      1640669.76      258039.352     1640585.203       258763.62
#Sta/Elev= 30
       0  860.44    29.2  860.09    97.2  858.62   116.7  858.38   223.6   858.6
   262.5  858.39   320.8  858.67   330.6  858.28   340.3  856.89     350  855.05
   359.7   856.5   369.4  859.12   379.2  861.39   388.9  862.48   398.6  862.82
   418.1  862.86   486.1  862.12   515.3  862.14   583.4  864.22   593.1  864.37
   612.5  864.25   622.2  864.45     632  865.44   651.4  868.73   670.8  871.41
   680.6  873.43   690.3  876.31   709.7  883.15   719.5  886.25   729.2  888.75
#Mann= 3 , 0 , 0
       0     .06       0   340.3    .045       0   359.7     .06       0
Bank Sta=340.3,359.7
XS Rating Curve= 0 ,0
Exp/Cntr=0.3,0.1

Chan Stop Cuts=-1
Use User Specified Reach Order=0
Composite Channel Slope=5